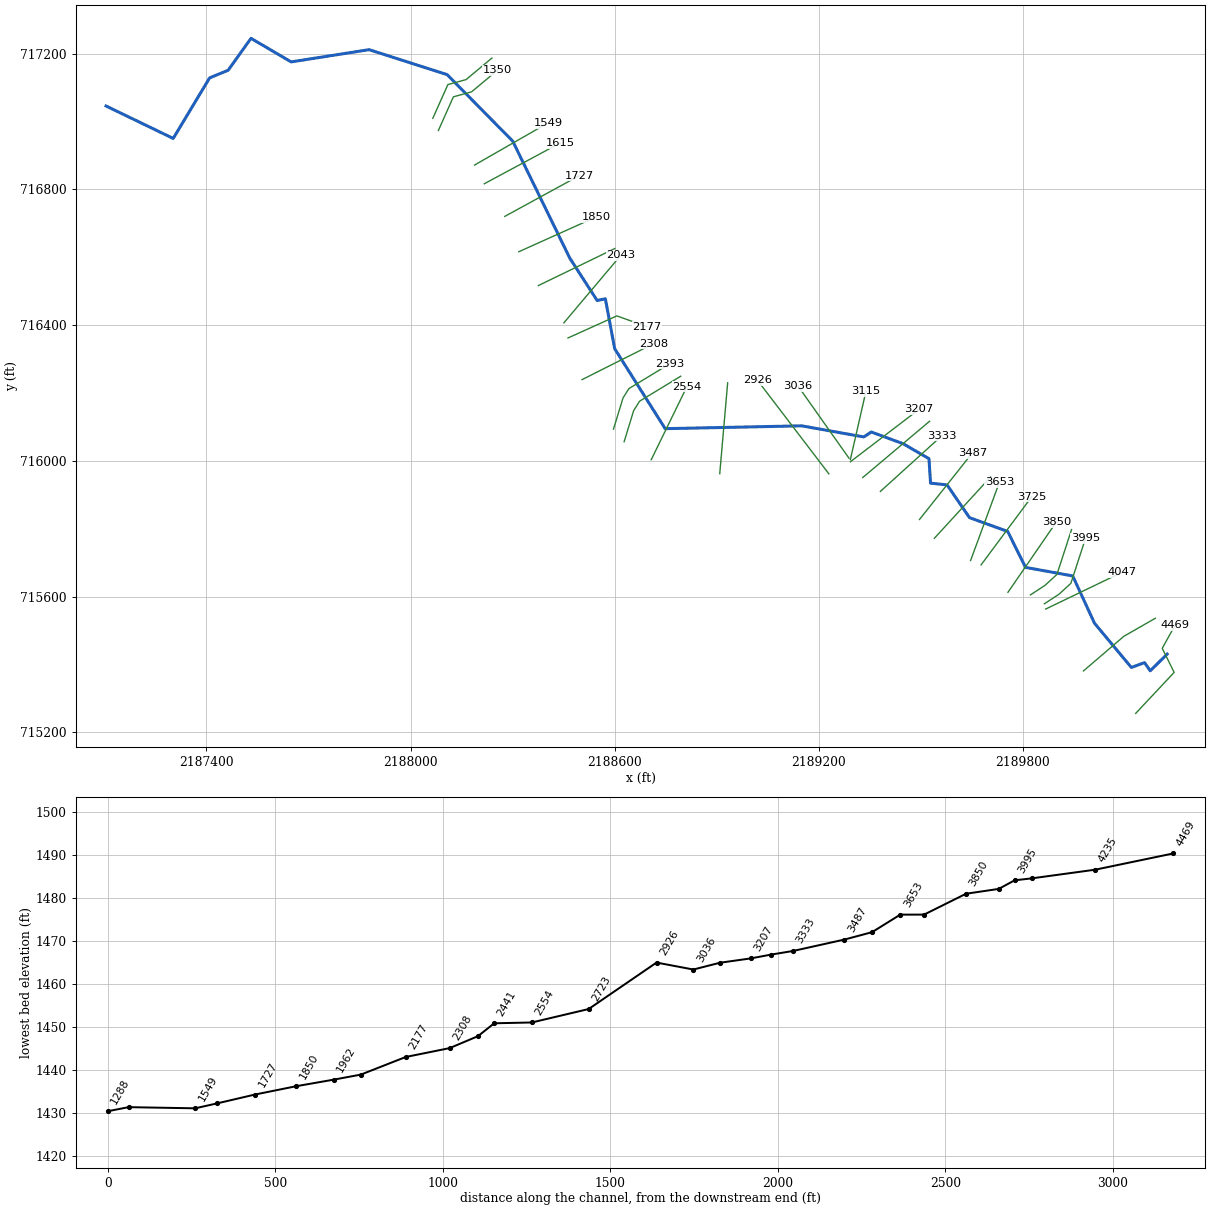
--- BUCKHANRT2.prj (project) ---

Proj Title=BUCKHANRT2
Current Plan=p01
Default Exp/Contr=0.3,0.1
English Units
Geom File=g01
Flow File=f01
Plan File=p01
Y Axis Title=Elevation
X Axis Title(PF)=Main Channel Distance
X Axis Title(XS)=Station
BEGIN DESCRIPTION:
---------- MODELED AS PART OF WVEMD CTP PROGRAM, 2023----------
Stream Name: Buckhannon River Tributary 2
Flood Zone:  AFH
Upshur County, WV
HEC-RAS Version: RAS 6.3
Vertical Datum: NAVD88
Projection: NAD 1983 StatePlane West Virginia S FIPS 4702 (US Feet)
Terrain: 1-meter LIDAR (FEMA Region III 3DEP collected 2016-2018)
Land Use: 2019 NLCD
Hydrologic Method:
WV SIR2010-5033 regression equations
Additional Model Notes:
None
END DESCRIPTION:
DSS Export Rating Curves= 0
DSS Export Rating Curve Sorted= 0
DSS Export Volume Flow Curves= 0
DXF OffsetX= 0
DXF OffsetY= 0
DXF ScaleX= 1
DXF ScaleY= 10

--- BUCKHANRT2.p01 (plan) ---

Plan Title=Floodplain
Program Version=4.10
Short Identifier=Floodplain
Geom File=g01
Flow File=f01
Subcritical Flow
K Sum by GR= 0
Std Step Tol= 0.01
Critical Tol= 0.01
Num of Std Step Trials= 20
Max Error Tol= 0.3
Flow Tol Ratio= 0.001
Split Flow NTrial= 30
Split Flow Tol= 0.02
Split Flow Ratio= 0.02
Log Output Level= 0
Friction Slope Method= 1
Unsteady Friction Slope Method= 2
Unsteady Bridges Friction Slope Method= 1
Parabolic Critical Depth
Global Vel Dist= 0 , 0 , 0
Global Log Level= 0
CheckData=True
Encroach Param=-1 ,0,0, 0
Computation Interval=1MIN
Output Interval=1HOUR
Run HTab= 0
Run UNet= 0
Run PostProcess= 0
Run WQNet= 0
UNET Theta= 1
UNET Theta Warmup= 1
UNET ZTol= 0.02
UNET ZSATol= 0.02
UNET MxIter= 20
UNET MaxInSteps= 0
UNET DtIC= 0
UNET DtMin= 0
UNET MaxCRTS= 20
UNET WFStab= 2
UNET SFStab= 1
UNET WFX= 1
UNET SFX= 1
UNET DSS MLevel= 4
UNET DZMax Abort= 100
UNET Convert EG Bridges= 0
UNET Use Existing IB Tables=-1
UNET Froude Reduction=False
UNET Froude Limit= 0.8
UNET Froude Power= 4
UNET Time Slicing=0,0, 5
UNET Junction Losses=0
Instantaneous Interval=1HOUR
Write IC File= 0
Write IC File at Sim End=0
Echo Input=False
Echo Parameters=False
Echo Output=False
Write Detailed= 0
WQ AD Non Conservative
WQ ULTIMATE=-1
WQ Max Comp Step=1HOUR
WQ Output Interval=15MIN
WQ Output Selected Increments= 0
WQ Output face flow=0
WQ Output face velocity=0
WQ Output face area=0
WQ Output face dispersion=0
WQ Output cell volume=0
WQ Output cell surface area=0
WQ Output cell continuity=0
WQ Output cumulative cell continuity=0
WQ Output face conc=0
WQ Output face dconc_dx=0
WQ Output face courant=0
WQ Output face peclet=0
WQ Output face adv mass=0
WQ Output face disp mass=0
WQ Output cell mass=0
WQ Output cell source sink temp=0
WQ Output cell source sink nsm=0
WQ Output MaxMinRange=-1
WQ Daily Max Min Mean=-1
WQ Daily Range=0
WQ Daily Time=0
WQ Create Restart=0
WQ Fixed Restart=0
WQ System Summary=0
WQ Use Fixed Temperature=0
Sorting and Armoring Iterations= 10
XS Update Threshold= 0.02
Hydraulics Update Threshold= 0.02
Energy Slope Method= 1
Volume Change Method= 1
XS Weighting Method= 0
Number of US Weighted Cross Sections= 1
Number of DS Weighted Cross Sections= 1
Upstream XS Weight=0
Main XS Weight=1
Downstream XS Weight=0
Number of DS XS's Weighted with US Boundary= 1
Upstream Boundary Weight= 1
Weight of XSs Associated with US Boundary= 0
Number of US XS's Weighted with DS Boundary= 1
Downstream Boundary Weight= 0.5
Weight of XSs Associated with DS Boundary= 0.5
Sediment Output Level= 3
Mass or Volume Output= 0
Output Increment Type= 1
Profile and TS Output Increment= 1
XS Output Flag= 0
XS Output Increment= 10
Disregard all LS=0
Disregard all Conn=0
Disregard all Breaches=0
Disregard all Pumps=0

--- BUCKHANRT2.f01 (steady flow) ---

Flow Title=Flows
Program Version=4.10
Number of Profiles= 1
Profile Names=01pct
River Rch & RM=BUCKHANRT2,Main            ,4469
    61.8
River Rch & RM=BUCKHANRT2,Main            ,2554
    69.4
River Rch & RM=BUCKHANRT2,Main            ,2393
    85.2
River Rch & RM=BUCKHANRT2,Main            ,2043
    92.7
River Rch & RM=BUCKHANRT2,Main            ,1350
     104
Boundary for River Rch & Prof#=BUCKHANRT2,Main            , 1
Up Type= 0
Dn Type= 3
Dn Slope=0.00108
DSS Import GetInterval= 0
DSS Import GetPeak= 0
DSS Import FillOption= 0

--- BUCKHANRT2.g01 (geometry) ---

Geom Title=Geometry
Program Version=6.30

River Reach=BUCKHANRT2      ,Main
Reach XY= 30
 2190223.9800272715430.4622449282190174.32723933715381.156897336
2190157.48704991715405.2887388472190118.77190427715391.052546844
 2190010.4384595715521.4345039282189946.37592359715660.844330087
2189807.66064985715686.0178361832189755.40353654715791.920511499
 2189643.0773176715832.5457583522189576.93145253715929.247008502
2189528.49388537 715934.281775342189523.81498019716006.477216765
2189447.76471612716050.6010965112189354.18845968716085.149911925
2189332.31350344716070.5666077732189149.67443302716103.257487267
2188748.37241411716094.9241705982188599.93504691716330.601192683
2188572.59126964716477.7367251812188548.37248603716472.788572356
2188467.90381494716597.7886504382188300.19548897716942.580283687
2188107.45045803717138.5514462742187878.05985025717212.133222267
2187648.89331385717176.1090161062187530.83777568717245.553431019
2187463.79329036717151.5378710032187409.33440979 717128.94342801
2187302.15516219716950.5044804362187104.87649865717046.059197473

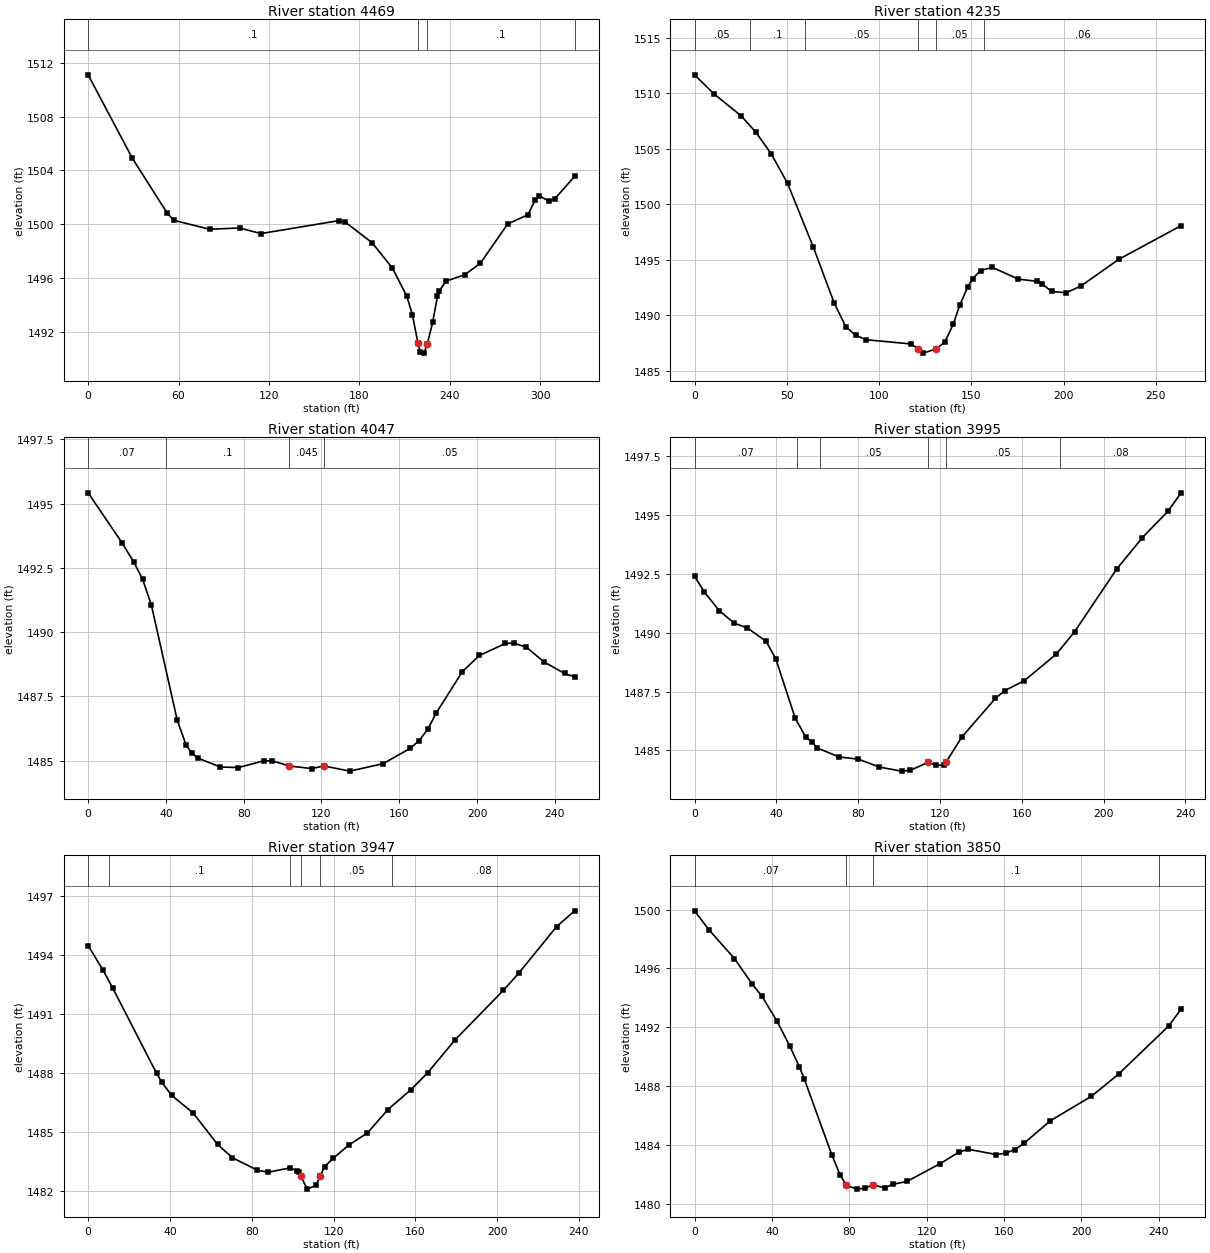
Type RM Length L Ch R = 1 ,4469    ,233.4,233.4,233.4
XS GIS Cut Line= 4
2190131.56752787715255.6787784152190244.57599827715376.554927138
2190209.52906757715447.364032011 2190247.4369722715516.027406433
#Sta/Elev= 30
       0 1511.11    29.4 1504.89    52.4 1500.83    56.8 1500.28    80.7 1499.61
   100.5 1499.71   114.7 1499.29   166.2 1500.25   170.6 1500.15   188.5 1498.61
   201.9 1496.73   211.5 1494.64   215.3 1493.22  218.971491.107   220.5 1490.47
     223 1490.39  225.191491.105   228.7 1492.69   231.9 1494.61   233.1 1495.03
   237.6 1495.75     250 1496.23   260.3 1497.07   278.5 1500.01   291.9 1500.69
   296.8  1501.8   299.6 1502.11     306 1501.68   309.6 1501.86322.9152 1503.55
#Mann= 4 ,-1,0
       0      .1       0  218.97    .045       0  225.19      .1       0
  322.92     .06       0
Bank Sta=218.97,225.19
XS Rating Curve= 0 ,0
Exp/Cntr(USF)=0,0
Exp/Cntr=0.3,0.1

Type RM Length L Ch R = 1 ,4235    ,188.6,188.6,188.6
XS GIS Cut Line= 3
2189977.96051307715380.7588017622190096.81762968715482.922522876
2190189.47972072715536.179216823
#Sta/Elev= 30
       0 1511.66    10.4 1509.96    25.2 1507.97    33.1 1506.51    41.6 1504.53
    50.4 1501.88    64.3 1496.16    75.6 1491.13      82 1488.96    87.3 1488.22
    92.7 1487.81   117.2 1487.43  121.121486.982   123.8  1486.6  130.911486.981
   135.6  1487.6   140.1 1489.18   143.7 1490.93   147.9 1492.52   150.6  1493.3
     155 1494.04   161.3 1494.32   175.5 1493.26   185.3 1493.07   188.3 1492.84
   193.4 1492.15   201.4 1492.04   209.4 1492.65   229.8 1495.04   263.6 1498.08
#Mann= 6 ,-1,0
       0     .05       0      30      .1       0      60     .05       0
  121.12    .045       0  130.91     .05       0  156.73     .06       0
Bank Sta=121.12,130.91
XS Rating Curve= 0 ,0
Exp/Cntr(USF)=0,0
Exp/Cntr=0.3,0.1

Type RM Length L Ch R = 1 ,4047    ,52.2,52.2,52.2
XS GIS Cut Line= 2
2189866.92743895715563.2334763492190092.22913627715671.950485851
#Sta/Elev= 30
       0 1495.42    17.4 1493.48    23.6 1492.71      28 1492.06    32.5 1491.06
    45.8 1486.58    50.3 1485.62    53.3 1485.29    56.3  1485.1      68 1484.75
    77.3 1484.73    90.2 1484.99    94.7 1484.99   103.5 1484.79   114.9 1484.69
   121.3 1484.79   134.6 1484.59   151.7 1484.88   165.7 1485.48   170.2 1485.78
   174.6 1486.21     179 1486.85   192.4 1488.46   201.2 1489.09   214.6 1489.56
     219 1489.57   225.4 1489.41   234.6 1488.83     245 1488.39250.1604 1488.26
#Mann= 4 ,-1,0
       0     .07       0      40      .1       0   103.5    .045       0
   121.3     .05       0
Bank Sta=103.5,121.3
XS Rating Curve= 0 ,0
Exp/Cntr(USF)=0,0
Exp/Cntr=0.3,0.1

Type RM Length L Ch R = 1 ,3995    ,47.5,47.5,47.5
XS GIS Cut Line= 4
2189863.00816004715578.6091001342189905.86430066715606.730465569
2189940.91123135715638.9164223292189983.85518825715771.193723199
#Sta/Elev= 30
       0 1492.39     4.7 1491.74      12 1490.94    19.3 1490.41    25.8  1490.2
    34.9 1489.64    39.7 1488.89    49.2 1486.37    54.4 1485.56    57.5 1485.36
    59.8 1485.11    70.7 1484.72    80.1 1484.63    90.4 1484.29   101.2 1484.12
   105.4 1484.15   114.31484.498     118 1484.36   122.2 1484.38  122.96  1484.5
   130.7 1485.57   147.1 1487.21   151.7 1487.54   161.2 1487.96   176.9 1489.09
   185.8 1490.04   206.4  1492.7     219 1494.04   231.6 1495.17   237.9 1495.94
#Mann= 6 ,-1,0
       0     .07       0      50      .1       0   61.26     .05       0
   114.3    .045       0  122.96     .05       0  178.84     .08       0
Bank Sta=114.3,122.96
XS Rating Curve= 0 ,0
Exp/Cntr(USF)=0,0
Exp/Cntr=0.3,0.1

Type RM Length L Ch R = 1 ,3947    ,97.4,97.4,97.4
XS GIS Cut Line= 4
2189822.08079789715604.915814472 2189864.9369385715633.037179907
 2189899.9838692715665.2231366682189942.92782609715797.500437537
#Sta/Elev= 30
       0 1494.48     7.3 1493.23    12.1 1492.31    33.5 1487.99      36 1487.55
    40.8 1486.88    51.3 1485.99    63.3 1484.39    70.6 1483.71    82.8 1483.08
    88.2 1482.98    98.8  1483.2   102.1 1483.05     103 1482.97  103.911482.786
   107.2 1482.12   111.4 1482.31  113.551482.788   115.6 1483.26   119.8 1483.68
   127.5 1484.36   136.6 1484.97   146.6 1486.16   157.7 1487.15   166.1 1488.03
   179.4 1489.69   203.1 1492.21   210.6 1493.08   229.1 1495.44   237.9 1496.24
#Mann= 6 ,-1,0
       0     .07       0      10      .1       0   98.84     .05       0
  103.91    .045       0  113.55     .05       0  148.84     .08       0
Bank Sta=103.91,113.55
XS Rating Curve= 0 ,0
Exp/Cntr(USF)=0,0
Exp/Cntr=0.3,0.1

Type RM Length L Ch R = 1 ,3850    ,125.2,125.2,125.2
XS GIS Cut Line= 2
2189756.06469899715612.5852767152189898.39815222715820.005886949
#Sta/Elev= 30
       0 1499.91     7.3 1498.64    20.6 1496.67    29.8 1494.93    34.7 1494.13
    42.6 1492.42    49.2 1490.73    54.1 1489.33    56.8 1488.46    70.9 1483.35
    75.3 1481.95    78.41481.263    83.9    1481      88 1481.06    92.1 1481.29
    98.3 1481.09   102.6 1481.33   109.8 1481.52   127.1 1482.74   136.6 1483.51
   141.4 1483.71     156 1483.35   160.8 1483.44   165.7 1483.69   170.5 1484.13
     184 1485.65   205.2 1487.31   219.2 1488.81   245.1 1492.08251.5594 1493.23
#Mann= 4 ,-1,0
       0     .07       0    78.4    .045       0    92.1      .1       0
     240     .08       0
Bank Sta=78.4,92.1
XS Rating Curve= 0 ,0
Exp/Cntr(USF)=0,0
Exp/Cntr=0.3,0.1

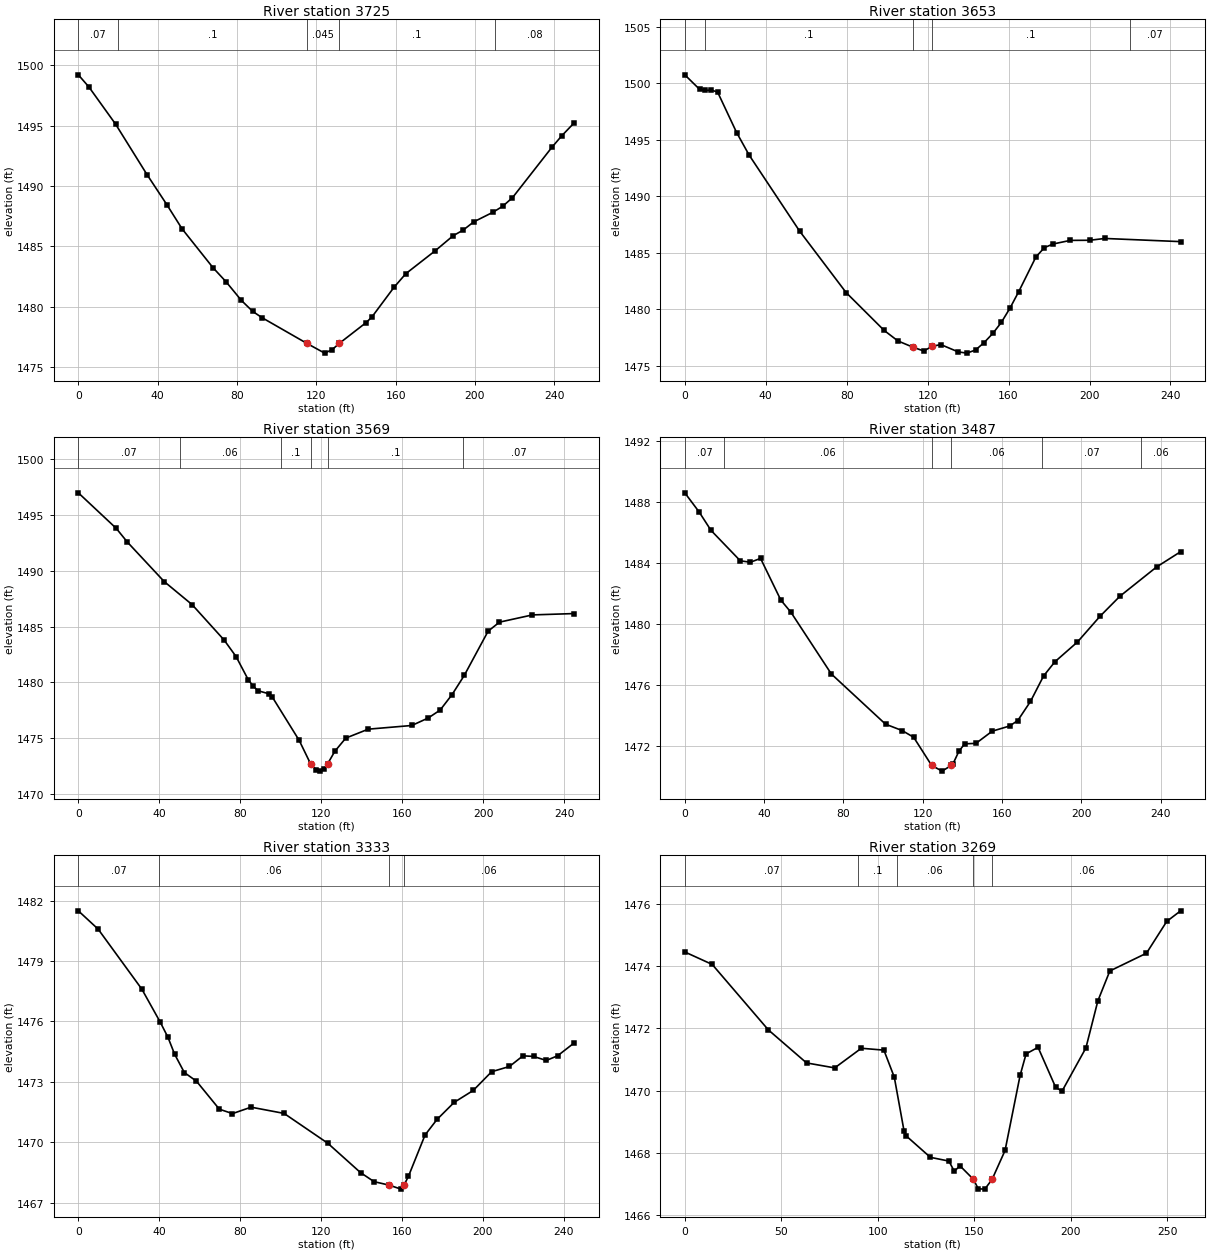
Type RM Length L Ch R = 1 ,3725    ,71.2,71.2,71.2
XS GIS Cut Line= 2
2189676.99979156715693.3686387312189825.88166194715894.202372634
#Sta/Elev= 29
       0  1499.2     5.3  1498.2    18.8 1495.11    34.6 1490.94    44.6 1488.45
    52.3 1486.44    67.9 1483.22    74.5 1482.05    82.2 1480.51    87.9  1479.6
    92.6 1479.08  115.251476.946   124.2 1476.14     128 1476.43  131.581476.947
   145.1 1478.67     148 1479.13   159.1 1481.58   165.1 1482.72     180 1484.63
     189 1485.87     194 1486.33   199.4 1487.02   208.9  1487.8   213.9  1488.3
   218.9 1489.02   238.8  1493.2   243.7 1494.14     250 1495.22
#Mann= 5 ,-1,0
       0     .07       0      20      .1       0  115.25    .045       0
  131.58      .1       0     210     .08       0
Bank Sta=115.25,131.58
XS Rating Curve= 0 ,0
Exp/Cntr(USF)=0,0
Exp/Cntr=0.3,0.1

Type RM Length L Ch R = 1 ,3653    ,84.1,84.1,84.1
XS GIS Cut Line= 2
2189646.22796561 715706.319628732189730.65411213715936.337803434
#Sta/Elev= 30
       0 1500.74     7.3 1499.46      10 1499.36    13.1 1499.39    16.2 1499.22
    25.6 1495.64    31.8 1493.64    56.7 1486.93    79.7 1481.49    98.5 1478.14
   105.3 1477.21   112.8 1476.65   118.1 1476.32   122.4 1476.75   126.6 1476.88
   135.1 1476.24   139.4 1476.13   143.7 1476.41   147.9 1477.06   152.2 1477.87
   156.4 1478.84   160.7 1480.11     165 1481.56   173.5 1484.63   177.7 1485.46
     182 1485.78   190.5  1486.1   200.1 1486.11   207.6 1486.27245.0227 1485.99
#Mann= 5 ,-1,0
       0     .07       0      10      .1       0   112.8    .045       0
   122.4      .1       0     220     .07       0
Bank Sta=112.8,122.4
XS Rating Curve= 0 ,0
Exp/Cntr(USF)=0,0
Exp/Cntr=0.3,0.1

Type RM Length L Ch R = 1 ,3569    ,82.4,82.4,82.4
XS GIS Cut Line= 2
2189539.56122991715771.6711245532189704.81993726715952.369226712
#Sta/Elev= 30
       0 1496.99    18.7 1493.81    24.2 1492.58    42.4 1489.04    56.2 1486.97
      72  1483.8    77.9 1482.32    83.9 1480.25    86.4 1479.66    88.8 1479.25
    94.2 1478.98    95.7 1478.72   109.1  1474.8   114.8 1472.67   117.6 1472.15
   119.4 1472.05   121.3 1472.23   123.11472.694   126.7 1473.83   132.1 1475.01
   143.2 1475.81   164.7 1476.14   172.8 1476.81   178.7 1477.52   184.6 1478.91
   190.6 1480.62   202.4 1484.59     208  1485.4   224.3 1486.05   244.9 1486.17
#Mann= 6 ,-1,0
       0     .07       0      50     .06       0     100      .1       0
   114.8    .045       0   123.1      .1       0     190     .07       0
Bank Sta=114.8,123.1
XS Rating Curve= 0 ,0
Exp/Cntr(USF)=0,0
Exp/Cntr=0.3,0.1

Type RM Length L Ch R = 1 ,3487    ,153.5,153.5,153.5
XS GIS Cut Line= 2
2189495.99041429715827.2010794282189651.13789325716023.234902458
#Sta/Elev= 30
       0 1488.58     7.2 1487.33    13.2 1486.12      28 1484.12    33.1 1484.03
    38.2 1484.28    48.4 1481.55    53.5 1480.75    73.9  1476.7   101.2 1473.41
   109.6 1472.99   115.4 1472.55  124.451470.707   129.7 1470.33  134.431470.707
   135.2  1470.8   138.2 1471.63   141.1 1472.12   146.8 1472.15     155 1472.95
   163.8 1473.29   167.9 1473.65   174.3  1474.9   180.9 1476.57   186.6  1477.5
     198  1478.8   209.4 1480.49   219.4  1481.8   237.9 1483.72     250 1484.72
#Mann= 6 ,-1,0
       0     .07       0      20     .06       0  124.45    .045       0
  134.43     .06       0     180     .07       0     230     .06       0
Bank Sta=124.45,134.43
XS Rating Curve= 0 ,0
Exp/Cntr(USF)=0,0
Exp/Cntr=0.3,0.1

Type RM Length L Ch R = 1 ,3333    ,64.5,64.5,64.5
XS GIS Cut Line= 2
2189380.91504041715909.9284091632189562.36659024716074.694759011
#Sta/Elev= 30
       0 1481.49     9.8 1480.58    31.4  1477.6    40.5 1475.96    44.3 1475.21
    47.6 1474.37    52.4 1473.46    58.4 1473.03    69.7 1471.64    76.2 1471.42
    85.4 1471.74   101.7 1471.43   123.3 1469.95   139.5 1468.49   146.2 1468.04
   153.6 1467.87   159.5 1467.67   161.1 1467.89   163.2 1468.31   171.4 1470.36
   177.3 1471.13   185.8 1471.98   195.2 1472.57   204.3  1473.5   213.1 1473.76
   219.8 1474.29     225 1474.26   231.3 1474.06   236.9 1474.29245.0972 1474.93
#Mann= 4 ,-1,0
       0     .07       0      40     .06       0   153.6    .045       0
   161.1     .06       0
Bank Sta=153.6,161.1
XS Rating Curve= 0 ,0
Exp/Cntr(USF)=0,0
Exp/Cntr=0.3,0.1

Type RM Length L Ch R = 1 ,3269    ,61.7,61.7,61.7
XS GIS Cut Line= 2
2189329.34555917715951.0376715642189525.73110674716116.863056028
#Sta/Elev= 30
       0 1474.45    14.2 1474.05    43.3 1471.95    63.1 1470.89    77.7 1470.73
    91.5 1471.36   103.2  1471.3   108.6 1470.43   113.6 1468.72   114.9 1468.54
   127.3 1467.86   136.9 1467.74   139.7 1467.41   142.6 1467.59  149.641467.152
   152.1 1466.85   155.5 1466.84  159.281467.153     166 1468.08   173.8 1470.49
   176.9 1471.18   183.1 1471.39   192.2 1470.11   195.5 1469.98   207.9 1471.37
   214.1 1472.88   220.3 1473.84   239.3 1474.41   249.8 1475.43     257 1475.77
#Mann= 5 ,-1,0
       0     .07       0      90      .1       0     110     .06       0
  149.64    .045       0  159.28     .06       0
Bank Sta=149.64,159.28
XS Rating Curve= 0 ,0
Exp/Cntr(USF)=0,0
Exp/Cntr=0.3,0.1

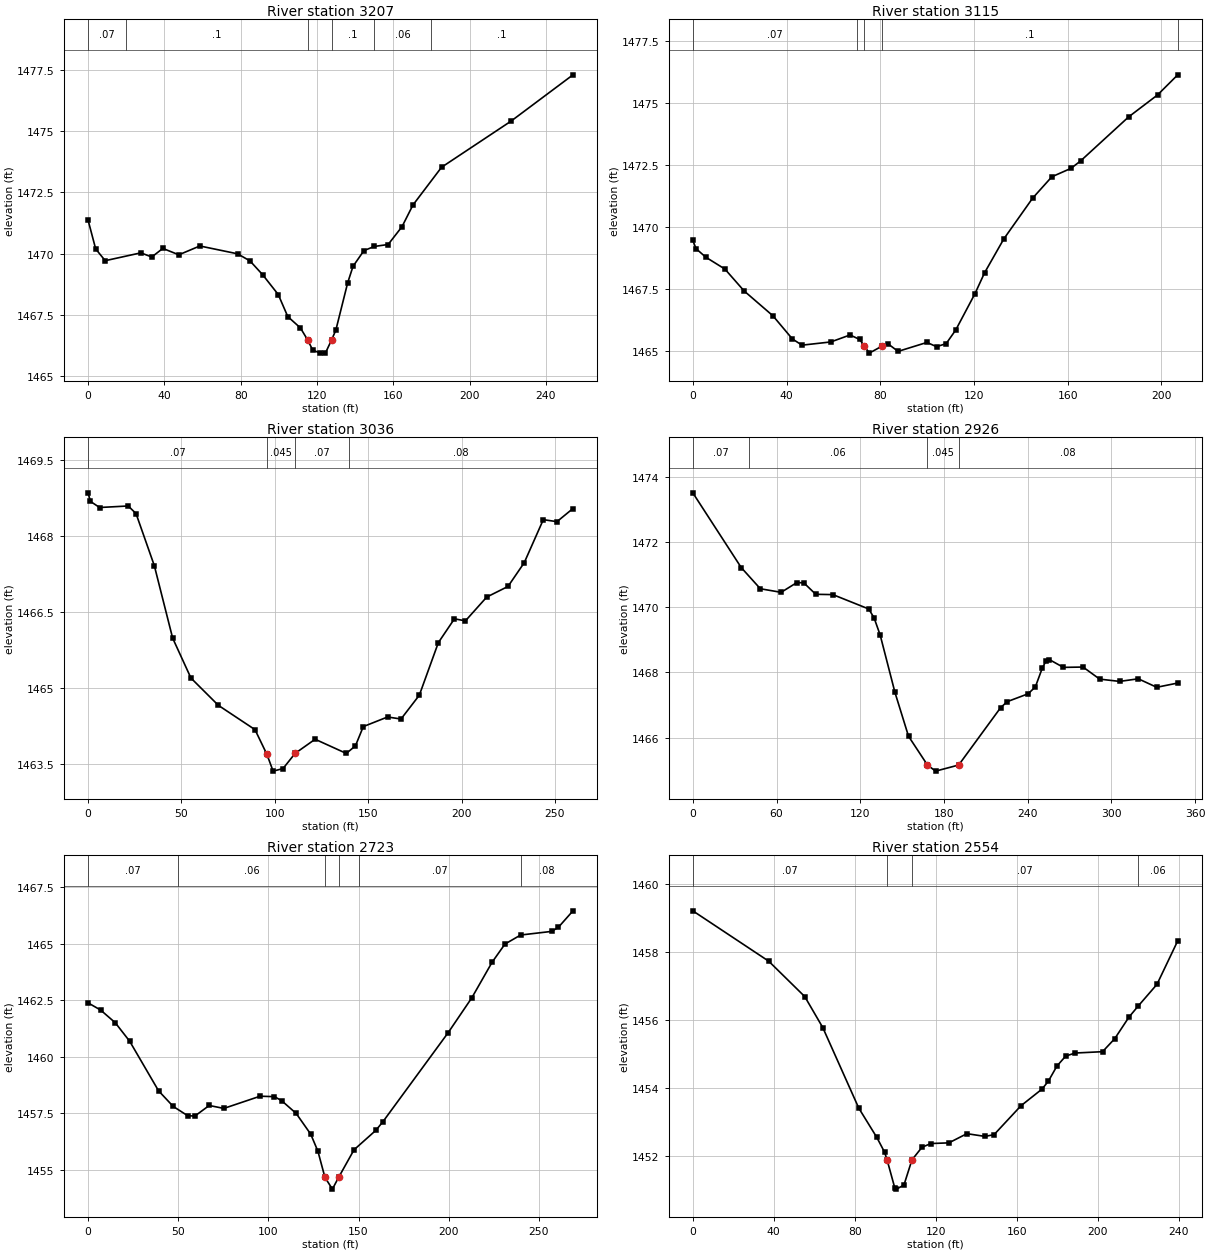
Type RM Length L Ch R = 1 ,3207    ,91.9,91.9,91.9
XS GIS Cut Line= 2
2189293.01726329715997.5647218522189494.88234472716152.037508301
#Sta/Elev= 30
       0 1471.37       4 1470.19       9 1469.71    27.7 1470.03    33.4 1469.86
    39.2 1470.21    47.6 1469.95    58.6 1470.31    78.4 1469.99    84.9  1469.7
    91.5 1469.14    99.7 1468.33   104.7 1467.43   111.3 1466.97  115.141466.475
   117.8 1466.06   121.8 1465.94   124.4 1465.94  127.641466.475   129.9 1466.88
   136.1 1468.81   138.9 1469.48   144.6 1470.12     150 1470.29   157.3 1470.37
   164.6  1471.1   170.3 1471.98   185.3 1473.52   221.7  1475.4   254.2 1477.29
#Mann= 6 ,-1,0
       0     .07       0      20      .1       0  115.14    .045       0
  127.64      .1       0     150     .06       0     180      .1       0
Bank Sta=115.14,127.64
XS Rating Curve= 0 ,0
Exp/Cntr(USF)=0,0
Exp/Cntr=0.3,0.1

Type RM Length L Ch R = 1 ,3115    ,79.4,79.4,79.4
XS GIS Cut Line= 2
2189292.79632799716003.7826590762189338.68062794716205.569296391
#Sta/Elev= 30
       0 1469.46     1.4 1469.13     5.5 1468.79    13.7 1468.31    21.9 1467.43
    34.2 1466.43    42.5  1465.5    46.6 1465.25    58.9 1465.38    67.1 1465.66
    71.2 1465.48   73.11 1465.23    75.3 1464.93    80.9 1465.22    83.5 1465.29
    87.6    1465    99.9 1465.36     104 1465.19   108.1 1465.31   112.2 1465.86
   120.4 1467.32   124.5 1468.16   132.7 1469.52     145 1471.16   153.2 1472.02
   161.4 1472.36   165.5 1472.66     186 1474.43   198.3 1475.31206.9377 1476.12
#Mann= 5 ,-1,0
       0     .07       0      70      .1       0   73.11    .045       0
    80.9      .1       0  206.94     .07       0
Bank Sta=73.11,80.9
XS Rating Curve= 0 ,0
Exp/Cntr(USF)=0,0
Exp/Cntr=0.3,0.1

Type RM Length L Ch R = 1 ,3036    ,110,110,110
XS GIS Cut Line= 2
2189288.57304563716008.1350308712189139.02376098716220.399965992
#Sta/Elev= 30
       0 1468.85     1.3 1468.68     6.2 1468.56    21.5 1468.59    25.7 1468.44
    35.5 1467.41    45.3 1465.98    55.1 1465.19    69.8 1464.65    89.4 1464.17
    95.8 1463.68    99.1 1463.35   104.4  1463.4   110.91463.701   121.6 1463.98
   138.3  1463.7   143.2 1463.85   147.4 1464.23   160.4 1464.42   167.6 1464.38
   177.4 1464.85   187.6 1465.89   196.2 1466.36   202.1 1466.32   213.5 1466.79
   224.9    1467   233.6 1467.47   243.8 1468.32   251.1 1468.28   259.7 1468.54
#Mann= 4 ,-1,0
       0     .07       0    95.8    .045       0   110.9     .07       0
     140     .08       0
Bank Sta=95.8,110.9
XS Rating Curve= 0 ,0
Exp/Cntr(USF)=0,0
Exp/Cntr=0.3,0.1

Type RM Length L Ch R = 1 ,2926    ,202.6,202.6,202.6
XS GIS Cut Line= 2
2189229.50998612715961.8368980992189019.04632716716238.445620118
#Sta/Elev= 30
       0  1473.5    34.7 1471.21    48.4 1470.56    63.3 1470.45    74.6 1470.75
    79.6 1470.74    88.1 1470.39   100.4 1470.38   126.1 1469.94   129.9 1469.67
   134.3 1469.14   144.9 1467.38   154.6 1466.04  168.181465.157     174 1464.97
  190.561465.157   220.7 1466.92   225.4  1467.1   240.3 1467.34   245.5 1467.55
   250.5 1468.13   253.2 1468.35   255.5 1468.39   265.6 1468.15   279.7 1468.16
   291.6 1467.79   305.9 1467.72   319.3  1467.8   332.5 1467.54347.5735 1467.67
#Mann= 4 ,-1,0
       0     .07       0      40     .06       0  168.18    .045       0
  190.56     .08       0
Bank Sta=168.18,190.56
XS Rating Curve= 0 ,0
Exp/Cntr(USF)=0,0
Exp/Cntr=0.3,0.1

Type RM Length L Ch R = 1 ,2723    ,169.7,169.7,169.7
XS GIS Cut Line= 2
2188908.79142049715962.1825421652188932.05168535716230.106333675
#Sta/Elev= 30
       0 1462.39       7 1462.07    15.1 1461.51    23.1 1460.69    39.1  1458.5
    47.2 1457.81    55.2  1457.4    59.2 1457.38    67.2 1457.85    75.3 1457.72
    95.4 1458.26   103.4 1458.24   107.4 1458.06   115.4  1457.5   123.5 1456.58
   127.5 1455.82  131.361454.672   135.5 1454.15  138.971454.671   147.5 1455.89
   159.6 1456.75   163.6 1457.14   199.7 1461.07   212.8 1462.61   224.1 1464.19
   231.2 1464.99   239.9 1465.39   257.1 1465.55   260.8 1465.73268.9316 1466.46
#Mann= 6 ,-1,0
       0     .07       0      50     .06       0  131.36    .045       0
  138.97     .06       0     150     .07       0     240     .08       0
Bank Sta=131.36,138.97
XS Rating Curve= 0 ,0
Exp/Cntr(USF)=0,0
Exp/Cntr=0.3,0.1

Type RM Length L Ch R = 1 ,2554    ,112.2,112.2,112.2
XS GIS Cut Line= 2
2188707.37080823716003.4238452622188812.27318582716218.791605314
#Sta/Elev= 30
       0  1459.2    37.5 1457.72    55.3 1456.68    64.2 1455.77      82  1453.4
    90.9 1452.54    94.7 1452.11   95.97 1451.88    99.8 1451.05   100.6 1451.02
   104.3 1451.14  108.251451.879   113.2 1452.25   117.6 1452.36   126.5 1452.38
   135.4 1452.65   144.3 1452.57   148.8 1452.62   162.1 1453.47   172.5 1453.96
   175.6 1454.19   179.9 1454.64   184.2 1454.93   188.8 1455.02   202.4 1455.06
   208.4 1455.44   215.5 1456.08     220  1456.4   229.3 1457.04239.5575 1458.32
#Mann= 4 ,-1,0
       0     .07       0   95.97    .045       0  108.25     .07       0
     220     .06       0
Bank Sta=95.97,108.25
XS Rating Curve= 0 ,0
Exp/Cntr(USF)=0,0
Exp/Cntr=0.3,0.1

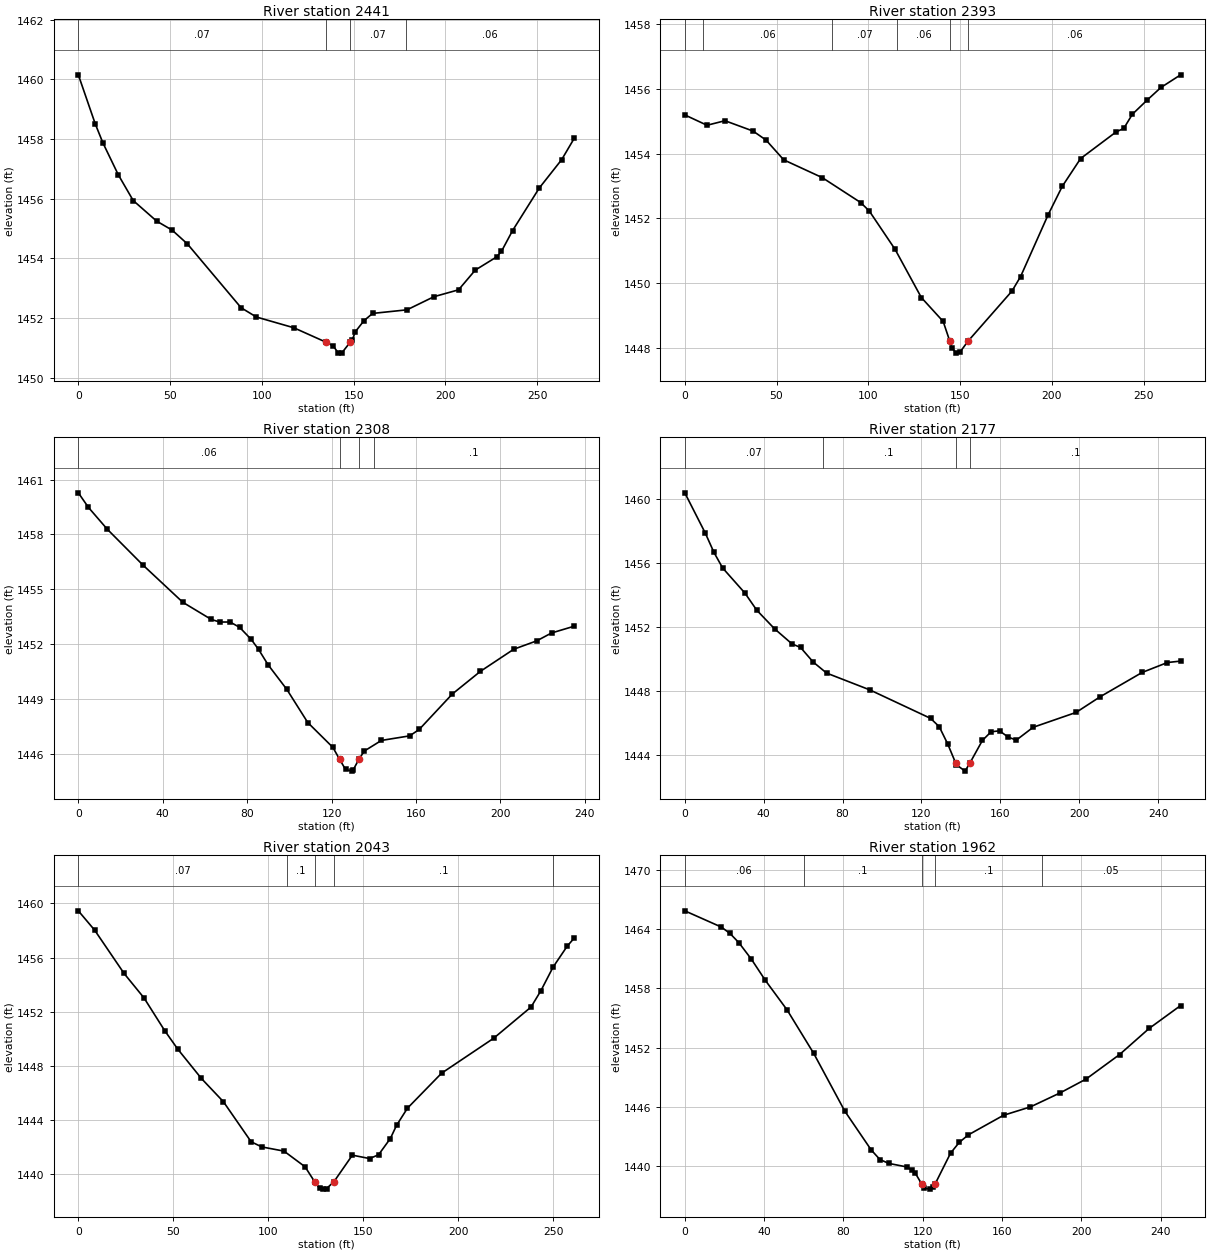
Type RM Length L Ch R = 1 ,2441    ,48.6,48.6,48.6
XS GIS Cut Line= 4
 2188627.7299135716056.3367496722188655.71433442716148.061971939
2188673.19806402  716175.87699632188793.97125043716249.538538932
#Sta/Elev= 30
       0 1460.15     9.2 1458.51    13.4 1457.87    21.8  1456.8    29.9 1455.94
    42.7 1455.25    51.1 1454.95    59.4 1454.49    88.7 1452.35      97 1452.04
   117.4 1451.68  135.061451.194   138.9 1451.07   141.6 1450.84   143.5 1450.83
  148.141451.194   149.3 1451.28     151 1451.55   155.7 1451.92   160.4 1452.16
   179.1 1452.28   193.8 1452.72   207.2 1452.95   216.3 1453.61   227.9 1454.05
   230.6 1454.24   236.6 1454.93   251.2 1456.36   263.4 1457.31   270.2 1458.02
#Mann= 4 ,-1,0
       0     .07       0  135.06    .045       0  148.14     .07       0
  178.75     .06       0
Bank Sta=135.06,148.14
XS Rating Curve= 0 ,0
Exp/Cntr(USF)=0,0
Exp/Cntr=0.3,0.1

Type RM Length L Ch R = 1 ,2393    ,84.4,84.4,84.4
XS GIS Cut Line= 4
 2188596.4351154716093.5809713422188624.41953632716185.306193609
2188641.90326592 716213.121217972188762.67645234716286.782760601
#Sta/Elev= 28
       0  1455.2    12.1 1454.88    21.9 1455.02    37.2  1454.7    44.3 1454.42
    53.9 1453.81    74.9 1453.26    95.8 1452.49   100.5 1452.23   114.6 1451.04
   128.9 1449.55   140.8 1448.81  144.361448.208   145.5    1448   147.9 1447.83
   150.2 1447.88  154.461448.208   178.3 1449.75     183  1450.2     198 1452.11
   205.7 1452.99   215.7 1453.85   235.2 1454.68   239.2 1454.78   243.9 1455.22
   251.8 1455.65   259.5 1456.05   270.2 1456.44
#Mann= 6 ,-1,0
       0     .07       0      10     .06       0      80     .07       0
   115.9     .06       0  144.36    .045       0  154.46     .06       0
Bank Sta=144.36,154.46
XS Rating Curve= 0 ,0
Exp/Cntr(USF)=0,0
Exp/Cntr=0.3,0.1

Type RM Length L Ch R = 1 ,2308    ,131.3,131.3,131.3
XS GIS Cut Line= 2
 2188503.9237729716239.4541948392188713.72852808716345.151287411
#Sta/Elev= 30
       0 1460.28     4.8 1459.48    13.7 1458.29    30.5 1456.34    49.5 1454.29
      63 1453.35      67 1453.21    71.9 1453.21    76.4 1452.92    81.9 1452.26
    85.4 1451.71    89.9 1450.87    98.8 1449.52   108.7 1447.71   120.6 1446.35
  123.821445.689   126.6 1445.14   129.5 1445.05   130.2 1445.11  132.881445.688
   135.5 1446.15   143.6 1446.73     157 1446.98   161.5 1447.33   177.2 1449.27
   190.5 1450.51   206.3 1451.72   217.2 1452.18   224.2 1452.61234.9253 1452.98
#Mann= 4 ,-1,0
       0     .06       0  123.82    .045       0  132.88     .06       0
     140      .1       0
Bank Sta=123.82,132.88
XS Rating Curve= 0 ,0
Exp/Cntr(USF)=0,0
Exp/Cntr=0.3,0.1

Type RM Length L Ch R = 1 ,2177    ,133.8,133.8,133.8
XS GIS Cut Line= 3
2188462.70884587716362.3115517852188606.40797734 716427.38783932
2188694.52220312 716395.63919741
#Sta/Elev= 30
       0 1460.38    10.4 1457.86    14.8 1456.65    19.2 1455.68    30.5 1454.11
    36.5 1453.04    45.5 1451.88    54.3 1450.94    58.7 1450.71    65.1  1449.8
    71.9 1449.11    93.8 1448.06   124.6 1446.28     129 1445.76   133.3 1444.68
  137.321443.491   137.7 1443.38   142.1 1442.98  144.581443.491   150.9  1444.9
   155.3 1445.44   159.6  1445.5   163.9 1445.11   168.1 1444.92   176.6 1445.72
   198.4 1446.65   210.6 1447.63   231.9 1449.15   244.7 1449.77   251.4 1449.86
#Mann= 4 ,-1,0
       0     .07       0      70      .1       0  137.32    .045       0
  144.58      .1       0
Bank Sta=137.32,144.58
XS Rating Curve= 0 ,0
Exp/Cntr(USF)=0,0
Exp/Cntr=0.3,0.1

Type RM Length L Ch R = 1 ,2043    ,81.5,81.5,81.5
XS GIS Cut Line= 2
2188450.47805366716406.7120483362188618.46885541716606.578027854
#Sta/Elev= 30
       0 1459.45     8.6 1458.02    24.1 1454.82    34.6 1453.01    45.5 1450.59
    52.4 1449.22    64.8 1447.06    76.4 1445.34      91 1442.38    96.6    1442
   108.3 1441.69   119.4 1440.53  124.441439.426     127 1438.95   128.6 1438.88
   130.7 1438.92  134.591439.428   144.3 1441.39   153.4 1441.14   158.1 1441.42
   164.3 1442.62   167.6  1443.6   173.3 1444.86   191.3 1447.45   218.7 1450.03
   238.4 1452.34   243.6 1453.55     250 1455.29   257.5 1456.85   261.1 1457.43
#Mann= 5 ,-1,0
       0     .07       0     110      .1       0  124.44    .045       0
  134.59      .1       0     250     .05       0
Bank Sta=124.44,134.59
XS Rating Curve= 0 ,0
Exp/Cntr(USF)=0,0
Exp/Cntr=0.3,0.1

Type RM Length L Ch R = 1 ,1962    ,112,112,112
XS GIS Cut Line= 2
2188375.63239871716516.7950981922188600.49758232716626.045494991
#Sta/Elev= 30
       0 1465.85    18.4 1464.21    22.8 1463.56    27.3 1462.62    33.6 1460.95
    40.6 1458.82    51.6 1455.82      65 1451.43    80.7 1445.58      94 1441.66
    98.4 1440.69   102.9  1440.3   111.8 1439.95   114.4 1439.64   116.2 1439.32
   119.41438.233   120.7  1437.8   123.4  1437.7   125.1 1437.89  126.251438.235
     134 1441.34   138.4 1442.43   142.9 1443.18   160.7 1445.17   174.3 1446.02
   189.3 1447.44   202.3 1448.83   219.2 1451.31   234.1 1453.95     250 1456.27
#Mann= 5 ,-1,0
       0     .06       0      60      .1       0   119.4    .045       0
  126.25      .1       0     180     .05       0
Bank Sta=119.4,126.25
XS Rating Curve= 0 ,0
Exp/Cntr(USF)=0,0
Exp/Cntr=0.3,0.1

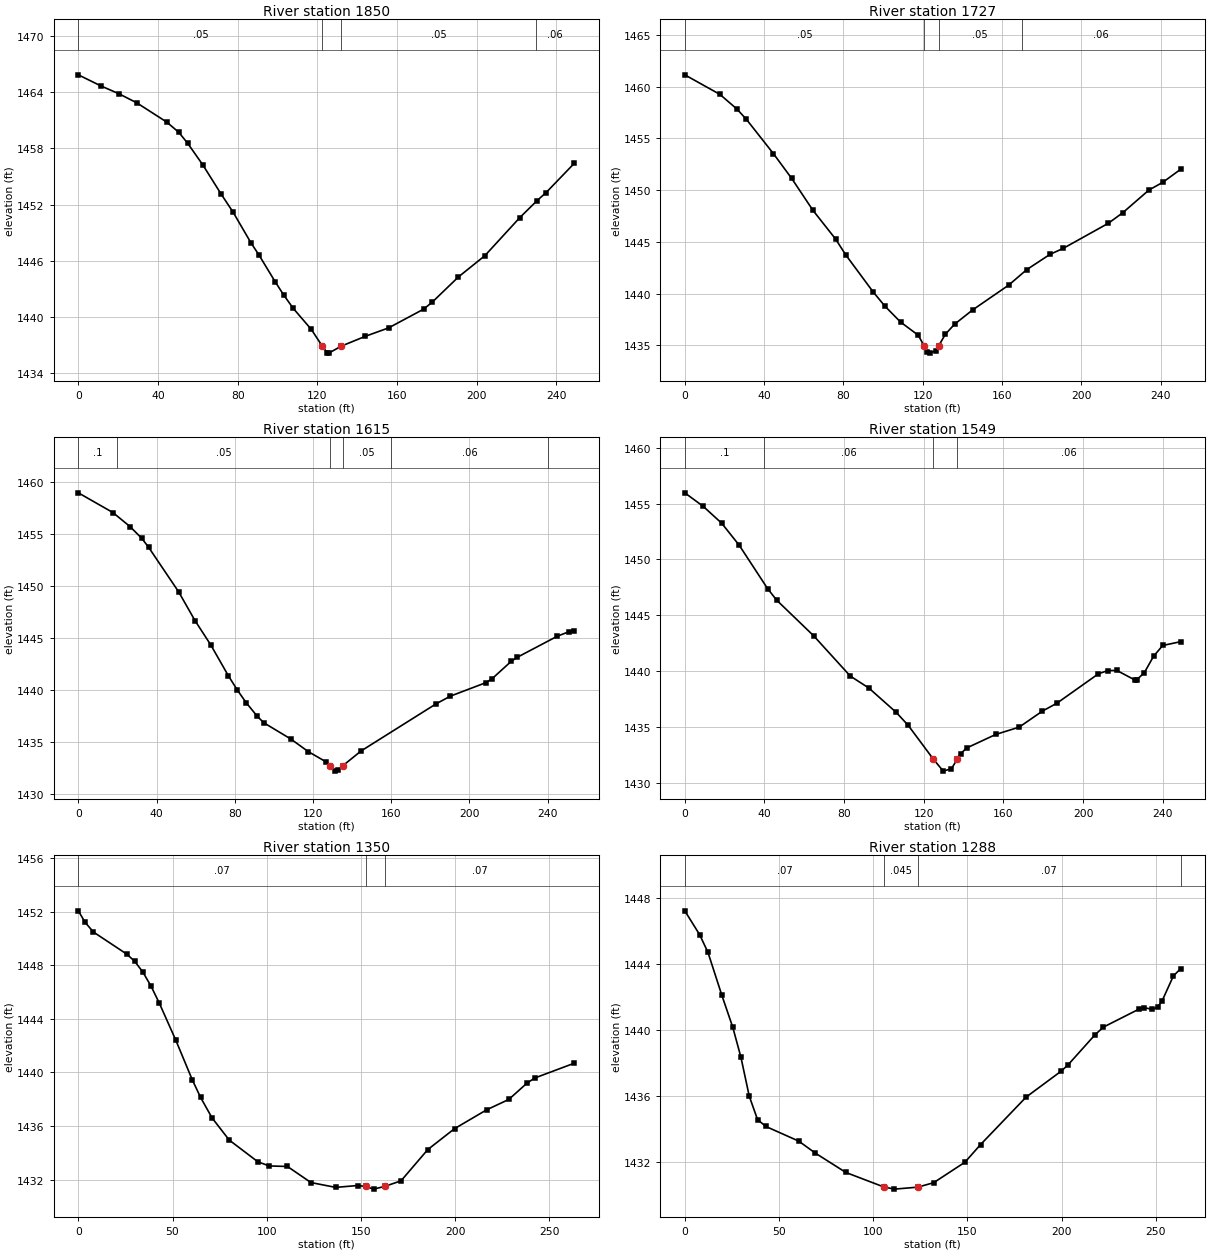
Type RM Length L Ch R = 1 ,1850    ,122.4,122.4,122.4
XS GIS Cut Line= 2
2188318.11839259716616.5044042322188545.13467917716718.861873493
#Sta/Elev= 30
       0 1465.85    11.4 1464.66    20.2 1463.85    29.3 1462.87    44.4 1460.81
    50.5 1459.71    54.9 1458.55    62.5 1456.25    71.6 1453.17    77.7 1451.21
    86.7 1447.93    90.7 1446.64    98.8  1443.8   103.2 1442.35   107.9 1440.95
     117  1438.7   122.6 1436.89   125.1 1436.17   126.1 1436.21   132.1 1436.92
   144.2 1437.97   155.8 1438.86   173.4 1440.86   177.8 1441.62   190.9  1444.3
   204.1 1446.55   221.6  1450.6   230.4 1452.44   234.9 1453.29     249  1456.4
#Mann= 4 ,-1,0
       0     .05       0   122.6    .045       0   132.1     .05       0
     230     .06       0
Bank Sta=122.6,132.1
XS Rating Curve= 0 ,0
Exp/Cntr(USF)=0,0
Exp/Cntr=0.3,0.1

Type RM Length L Ch R = 1 ,1727    ,112.5,112.5,112.5
XS GIS Cut Line= 2
2188276.94197968716720.6588647372188496.16736992716840.826365646
#Sta/Elev= 30
       0 1461.13    17.7 1459.24    26.3 1457.82    31.1 1456.82    44.7 1453.51
    53.9 1451.12    64.6 1448.04      76 1445.27    81.2 1443.72    94.9 1440.17
   100.9 1438.78   108.8 1437.24   117.7 1435.97  120.741434.922   122.3 1434.39
   123.6 1434.24   126.5 1434.47  127.951434.924   131.4 1436.07     136 1437.03
   145.1 1438.41   163.3 1440.81   172.5 1442.32   184.2 1443.79   190.7 1444.35
   213.5 1446.78   220.8  1447.8   234.1 1450.01   240.9 1450.73     250    1452
#Mann= 4 ,-1,0
       0     .05       0  120.74    .045       0  127.95     .05       0
     170     .06       0
Bank Sta=120.74,127.95
XS Rating Curve= 0 ,0
Exp/Cntr(USF)=0,0
Exp/Cntr=0.3,0.1

Type RM Length L Ch R = 1 ,1615    ,66.2,66.2,66.2
XS GIS Cut Line= 2
2188216.58316815716816.8680519942188439.88171078716937.046087093
#Sta/Elev= 30
       0 1458.98    17.7 1457.08    26.5 1455.72    32.4 1454.61    35.9 1453.75
    51.3 1449.45    59.7 1446.67    67.7 1444.35    76.7 1441.38    81.3    1440
    85.8 1438.79    91.5 1437.47    94.9 1436.84   108.6 1435.29   117.6 1434.07
   126.7 1433.08  128.691432.712   131.3 1432.19   132.8 1432.26  135.281432.713
   144.6 1434.13     183 1438.67   190.3 1439.41   208.5 1440.71   211.7  1441.1
   221.4 1442.76   224.4 1443.14     245 1445.18   250.9 1445.61253.5843 1445.68
#Mann= 6 ,-1,0
       0      .1       0      20     .05       0  128.69    .045       0
  135.28     .05       0     160     .06       0     240     .07       0
Bank Sta=128.69,135.28
XS Rating Curve= 0 ,0
Exp/Cntr(USF)=0,0
Exp/Cntr=0.3,0.1

Type RM Length L Ch R = 1 ,1549    ,198.9,198.9,198.9
XS GIS Cut Line= 2
 2188188.0993278716871.9979468732188403.96237013716996.162765862
#Sta/Elev= 30
       0 1455.97     9.3 1454.75    18.5 1453.25    27.3 1451.28    41.6 1447.38
    46.2 1446.34    64.7 1443.16    83.1 1439.55    92.4 1438.48   106.2 1436.29
   112.2 1435.13   124.81432.107   129.8 1431.03   133.9 1431.25  136.881432.106
   138.5 1432.58   141.5  1433.1   156.2 1434.32   167.9 1434.97   179.6 1436.41
   186.9 1437.12   207.7 1439.75   212.4 1440.04     217 1440.05   226.2 1439.18
     227 1439.22   230.8 1439.86   235.4 1441.32     240 1442.29     249 1442.63
#Mann= 4 ,-1,0
       0      .1       0      40     .06       0   124.8    .045       0
  136.88     .06       0
Bank Sta=124.8,136.88
XS Rating Curve= 0 ,0
Exp/Cntr(USF)=0,0
Exp/Cntr=0.3,0.1

Type RM Length L Ch R = 1 ,1350    ,62,62,62
XS GIS Cut Line= 4
2188081.67363197716973.874839784 2188125.8681352717073.118636511
2188179.36674438717087.8501375872188255.35027625717151.428194865
#Sta/Elev= 30
       0 1452.06     3.6  1451.2       8 1450.48    25.6 1448.84    29.9  1448.3
    34.3 1447.48    38.6 1446.44      43 1445.17    51.8 1442.39    60.5 1439.45
    64.9 1438.14      71 1436.61    80.1 1434.96    95.3 1433.34   101.3 1433.03
     111 1432.99   123.5 1431.79   136.6 1431.43   148.4 1431.57   152.5  1431.5
   156.7  1431.3   162.6  1431.5   171.3 1431.92   185.5 1434.25   199.7 1435.81
   216.8 1437.22   228.5 1437.99   238.2 1439.21   242.3 1439.59263.2031 1440.69
#Mann= 3 ,-1,0
       0     .07       0   152.5    .045       0   162.6     .07       0
Bank Sta=152.5,162.6
XS Rating Curve= 0 ,0
Exp/Cntr(USF)=0,0
Exp/Cntr=0.3,0.1

Type RM Length L Ch R = 1 ,1288    ,15.8,15.8,15.8
XS GIS Cut Line= 4
2188065.39144657717009.928250314 2188109.5859498 717109.17204704
2188163.08455898717123.9035481172188239.06809085717187.481605395
#Sta/Elev= 30
       0 1447.22     7.9 1445.77    12.3  1444.7    19.7 1442.09    25.5 1440.15
    29.8 1438.34    34.2 1435.99    38.6 1434.57      43 1434.15    60.5 1433.26
    69.2 1432.54    85.5 1431.36  105.68 1430.48   111.3 1430.35   123.7 1430.47
   132.1 1430.74   148.7 1431.98     157 1433.05   181.2 1435.93   199.9 1437.51
   203.5 1437.89   217.7  1439.7   222.2 1440.17   240.9 1441.25   243.8 1441.35
   248.2 1441.25     251 1441.38   253.4 1441.77   259.4 1443.28263.2031 1443.71
#Mann= 4 ,-1,0
       0     .07       0  105.68    .045       0   123.7     .07       0
   263.2     .06       0
Bank Sta=105.68,123.7
XS Rating Curve= 0 ,0
Exp/Cntr(USF)=0,0
Exp/Cntr=0.3,0.1