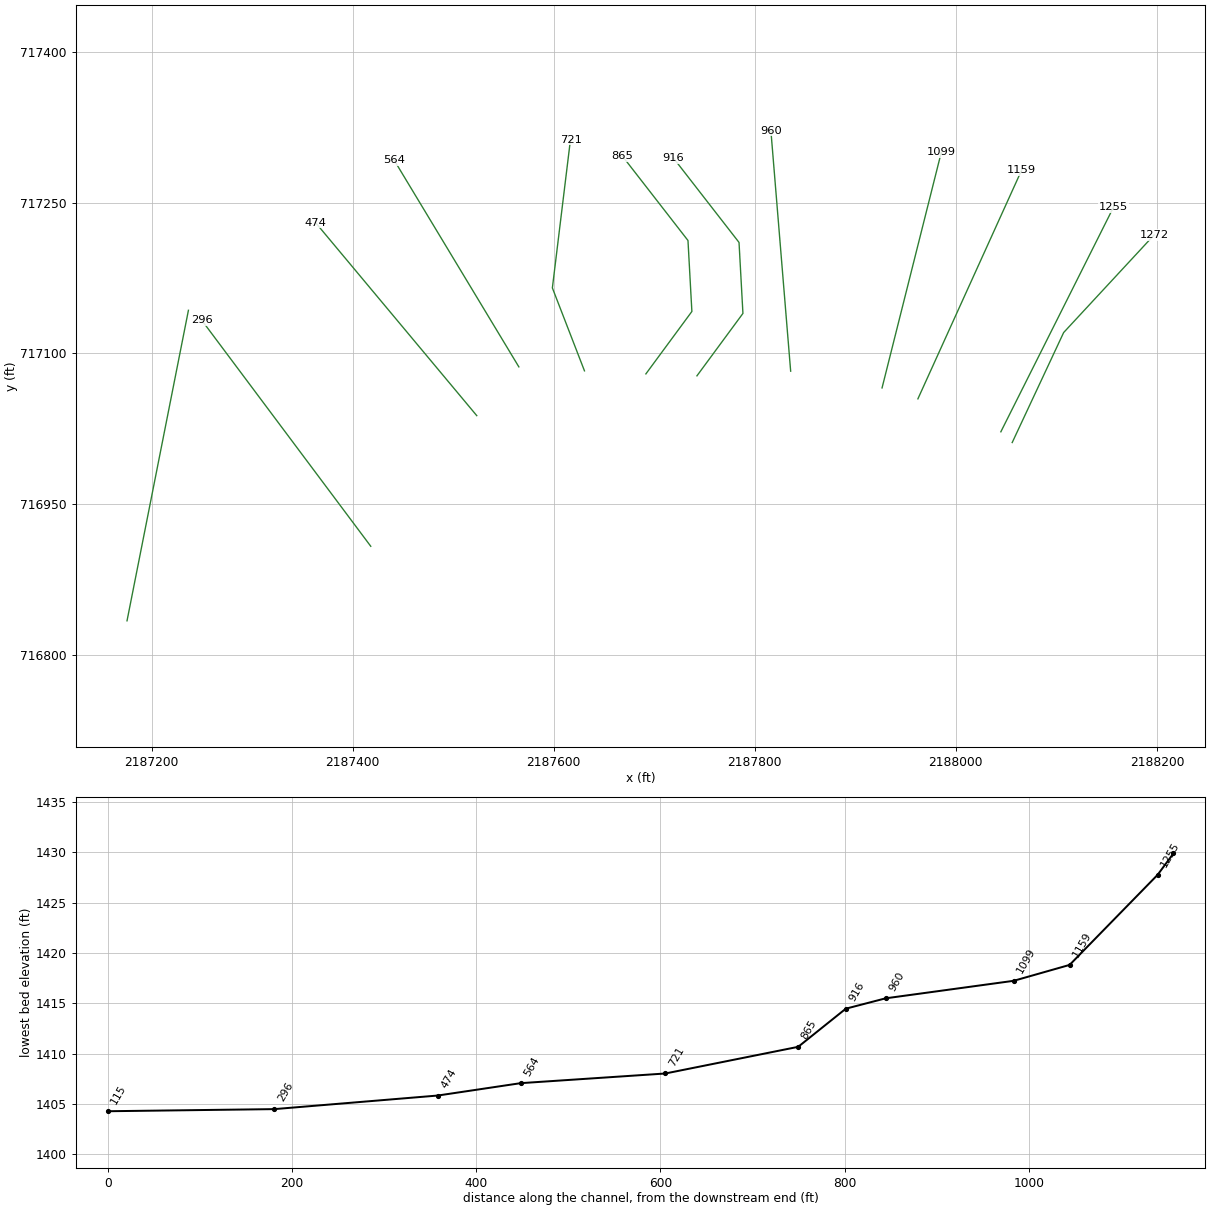
HEC-RAS study BUCKHANRT2.prj: BUCKHANRT2

--- BUCKHANRT2.g01 (geometry) --- (continued)

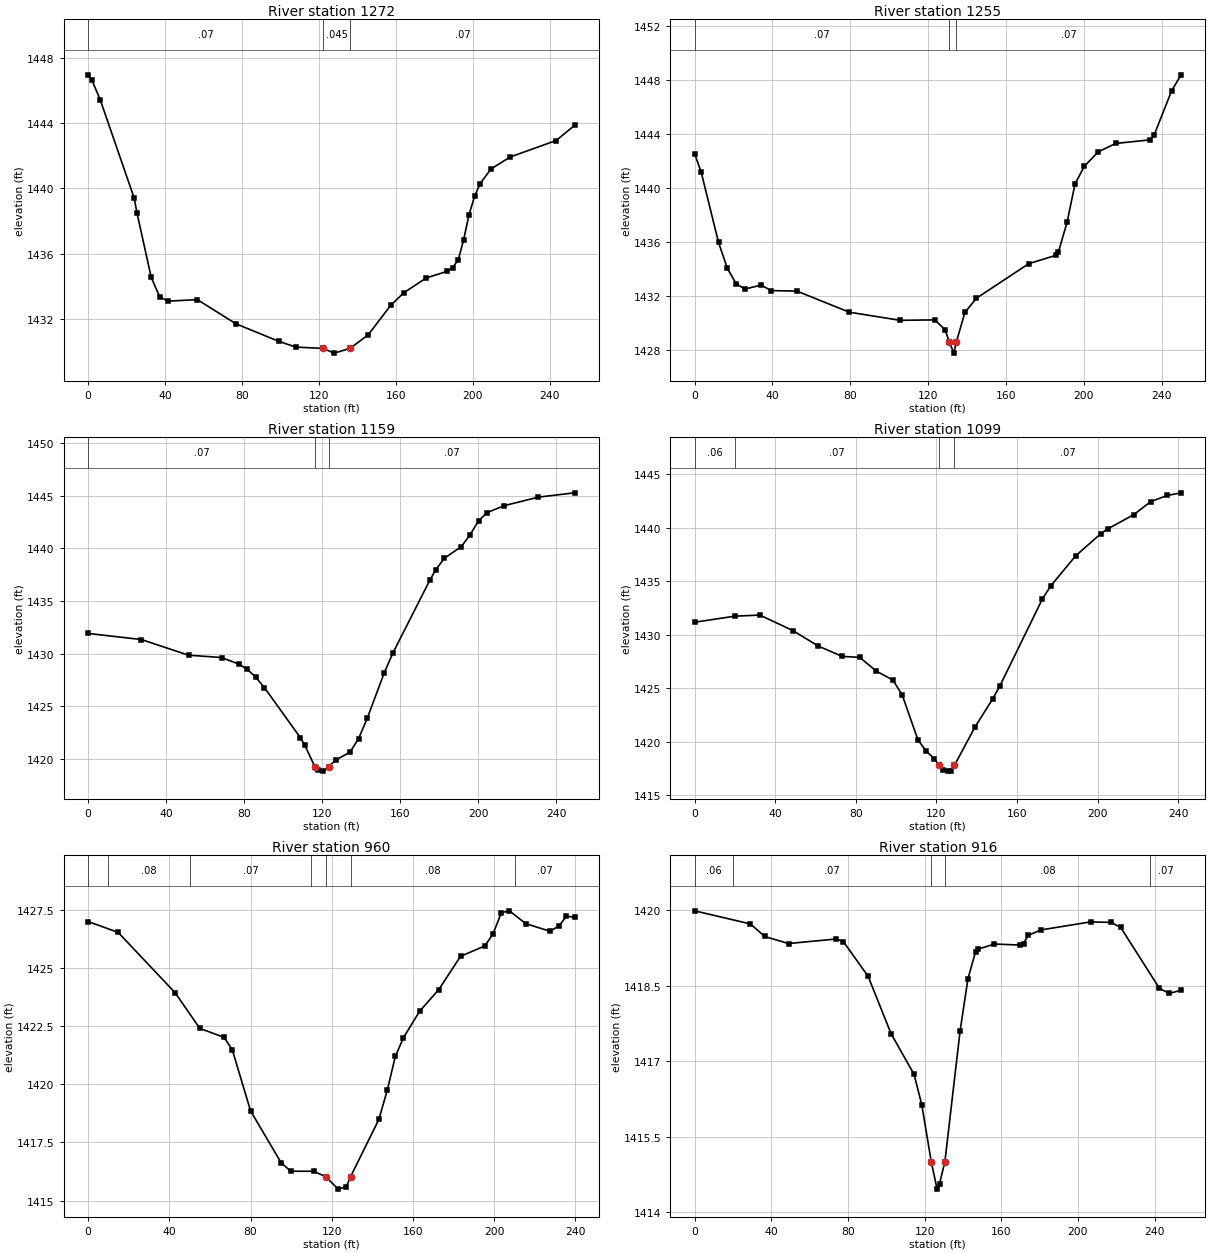
Type RM Length L Ch R = 1 ,1272    ,17.2,17.2,17.2
XS GIS Cut Line= 3
2188056.08734063717011.4789346382188107.25992332717120.802179469
 2188197.1996141 717217.71994971
#Sta/Elev= 30
       0 1446.96     1.9 1446.65     6.3 1445.43      24 1439.38    25.4 1438.49
    32.8 1434.54    37.2 1433.34    41.6 1433.08    56.8 1433.17      77 1431.68
      99 1430.62   107.9 1430.26  122.081430.181   127.9 1429.89   136.21430.181
   145.6 1431.01   157.3 1432.82   164.1 1433.59   175.8  1434.5   186.7 1434.91
   189.6 1435.14   192.4 1435.61   195.2 1436.83     198 1438.37   200.9  1439.5
   203.7 1440.27   209.4 1441.18   219.4 1441.92   243.3 1442.93252.9274 1443.86
#Mann= 3 ,-1,0
       0     .07       0  122.08    .045       0   136.2     .07       0
Bank Sta=122.08,136.2
XS Rating Curve= 0 ,0
Exp/Cntr(USF)=0,0
Exp/Cntr=0.3,0.1

Type RM Length L Ch R = 1 ,1255    ,95.5,95.5,95.5
XS GIS Cut Line= 2
 2188044.7832148717022.1464093112188156.95255149717245.569863557
#Sta/Elev= 30
       0 1442.53     3.4 1441.15    12.3 1435.96    16.8 1434.05    21.3 1432.91
    25.8  1432.5    34.3  1432.8    39.2 1432.39    52.6 1432.35    79.5 1430.79
   105.6 1430.19   123.5 1430.22   128.7 1429.49  130.971428.568   133.2 1427.76
  134.491428.572   138.9 1430.77   144.8 1431.82   171.7 1434.38   185.9 1435.01
   186.9 1435.22   191.4 1437.44   195.5 1440.29   200.3 1441.59   207.4 1442.66
   216.4 1443.28   234.2 1443.55   236.1 1443.88   245.1 1447.17     250 1448.36
#Mann= 3 ,-1,0
       0     .07       0  130.97    .045       0  134.49     .07       0
Bank Sta=130.97,134.49
XS Rating Curve= 0 ,0
Exp/Cntr(USF)=0,0
Exp/Cntr=0.3,0.1

Type RM Length L Ch R = 1 ,1159    ,60.7,60.7,60.7
XS GIS Cut Line= 2
2187962.27093904717054.8980957062188065.39144657 717282.07334915
#Sta/Elev= 30
       0 1431.91    27.3 1431.33    51.5 1429.84    68.4 1429.62    77.2    1429
    81.6  1428.5      86 1427.74    90.4 1426.76   108.9 1421.98   111.1 1421.28
  116.261419.238     118  1418.9   120.7 1418.81  123.331419.238     127 1419.87
   134.3 1420.61   138.7 1421.91   143.1 1423.82   151.9 1428.19   156.3 1430.05
   175.4 1437.04   178.2 1437.94   182.6 1439.05   191.4 1440.18   195.8 1441.28
   200.2 1442.62   204.6 1443.41   213.4 1444.07   230.9 1444.88249.4843 1445.29
#Mann= 3 ,-1,0
       0     .07       0  116.26    .045       0  123.33     .07       0
Bank Sta=116.26,123.33
XS Rating Curve= 0 ,0
Exp/Cntr(USF)=0,0
Exp/Cntr=0.3,0.1

Type RM Length L Ch R = 1 ,1099    ,139,139,139
XS GIS Cut Line= 2
2187926.60519959717065.7528859722187985.53120389717299.906218874
#Sta/Elev= 30
       0 1431.16      20 1431.73    32.4 1431.83    48.9 1430.37    61.3 1428.94
    73.3 1427.96    81.9 1427.88    90.2 1426.59    98.4 1425.75     103 1424.38
   110.8 1420.18   114.9  1419.1     119 1418.39  121.31 1417.77   123.1 1417.29
     126 1417.23   127.3 1417.24  128.981417.769   139.2 1421.37   147.9 1423.97
   151.4 1425.16   172.6 1433.33   176.8 1434.57   189.1 1437.37   201.5 1439.43
   205.1  1439.9     218 1441.23   226.3 1442.44   234.5 1443.02 241.454 1443.27
#Mann= 4 ,-1,0
       0     .06       0      20     .07       0  121.31    .045       0
  128.98     .07       0
Bank Sta=121.31,128.98
XS Rating Curve= 0 ,0
Exp/Cntr(USF)=0,0
Exp/Cntr=0.3,0.1

Type RM Length L Ch R = 1 ,960     ,43.2,43.2,43.2
XS GIS Cut Line= 2
2187835.69047598 717082.412245382187816.04381577 717321.20973518
#Sta/Elev= 30
       0 1427.01    14.8 1426.54    42.9 1423.94      55 1422.41      67 1422.02
      71 1421.49      80 1418.86    95.1 1416.62    99.8 1416.26   111.1 1416.26
  116.941416.027   123.2 1415.49   127.2  1415.6  129.261416.027   143.2 1418.49
   147.3 1419.74   151.3  1421.2   155.3 1422.01   163.3 1423.15   172.7 1424.08
   183.4 1425.51   195.4 1425.96   199.4 1426.47   203.5 1427.39   207.5 1427.47
   215.5 1426.92   227.5 1426.59     232 1426.83   235.6 1427.24239.6043 1427.19
#Mann= 7 ,-1,0
       0     .06       0      10     .08       0      50     .07       0
     110     .08       0  116.94    .045       0  129.26     .08       0
     210     .07       0
Bank Sta=116.94,129.26
XS Rating Curve= 0 ,0
Exp/Cntr(USF)=0,0
Exp/Cntr=0.3,0.1

Type RM Length L Ch R = 1 ,916     ,51.7,51.7,51.7
XS GIS Cut Line= 4
2187742.46143613717077.7706894822187788.20662368717139.798062436
2187784.32991287717210.3541991722187719.20117127 717294.09115266
#Sta/Elev= 29
       0 1419.99    29.1 1419.73    36.6 1419.48      49 1419.34    73.8 1419.43
    77.6 1419.38    90.5 1418.69   102.5 1417.55   114.5 1416.74   118.5 1416.14
  123.471415.005   126.5 1414.46   127.8 1414.57  130.581415.005   138.5  1417.6
   142.6 1418.64   146.6 1419.18     148 1419.23   156.4 1419.33   169.8 1419.31
   171.6 1419.34     174  1419.5   180.6 1419.61   206.6 1419.77   217.2 1419.76
   222.3 1419.66   242.5 1418.45   247.6 1418.35   253.8 1418.41
#Mann= 5 ,-1,0
       0     .06       0      20     .07       0  123.47    .045       0
  130.58     .08       0  237.73     .07       0
Bank Sta=123.47,130.58
XS Rating Curve= 0 ,0
Exp/Cntr(USF)=0,0
Exp/Cntr=0.3,0.1

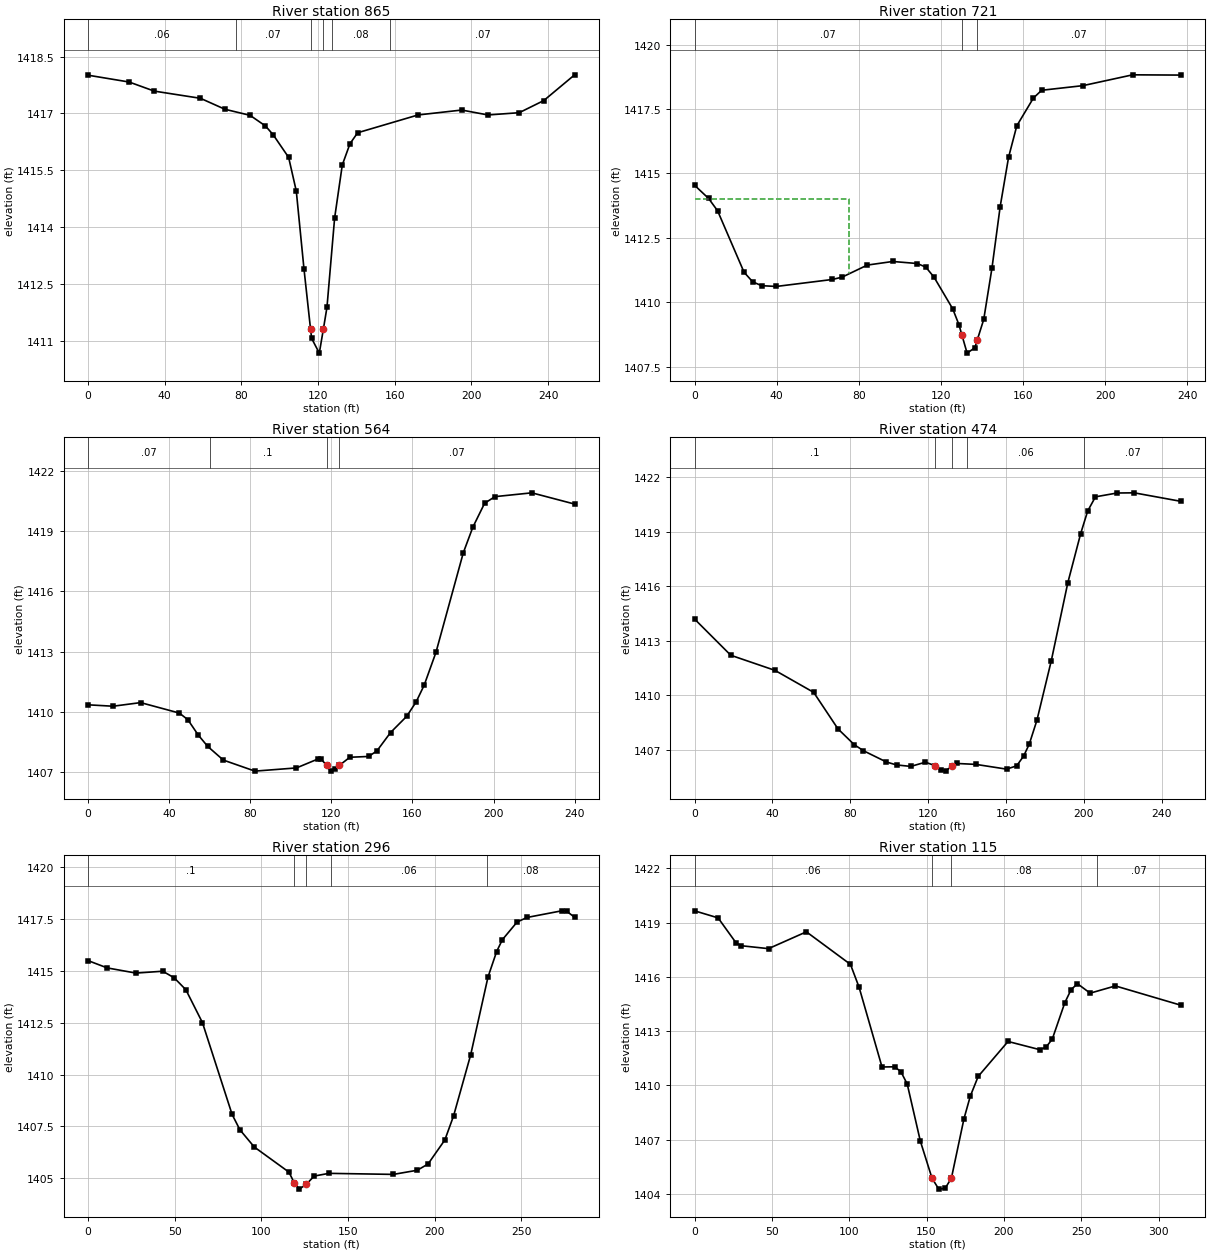
Type RM Length L Ch R = 1 ,865     ,144.2,144.2,143.2
XS GIS Cut Line= 4
2187691.67652452717079.7090448872187737.42171208717141.736417841
2187733.54500127717212.2925545762187668.41625967717296.029508064
#Sta/Elev= 26
       0 1418.01    21.4 1417.83    34.5 1417.59    58.6  1417.4    71.4 1417.11
    84.5 1416.95    92.5 1416.67    96.5 1416.44   104.6 1415.84   108.6 1414.95
   112.6  1412.9  116.031411.307   116.6 1411.06   120.6 1410.67  122.741411.307
   124.6 1411.88   128.6 1414.24   132.6 1415.64   136.6  1416.2   140.6 1416.49
   172.1 1416.96   194.9 1417.09   208.6 1416.96   224.9 1417.02   237.7 1417.34
   253.8 1418.02
#Mann= 6 ,-1,0
       0     .06       0   77.07     .07       0  116.03    .045       0
  122.74     .07       0  127.07     .08       0  157.73     .07       0
Bank Sta=116.03,122.74
XS Rating Curve= 0 ,0
Exp/Cntr(USF)=0,0
Exp/Cntr=0.3,0.1

Type RM Length L Ch R = 1 ,721     ,154.8,157,156.6
XS GIS Cut Line= 3
2187630.56506067717082.7439384292187598.64645925717165.142866066
2187616.64320583717312.546493285
#Sta/Elev= 30
       0 1414.54     6.8 1414.03    11.2 1413.55    24.1 1411.16    28.3 1410.79
    32.6 1410.64    39.8 1410.61      67 1410.88    71.8 1410.97    84.1 1411.44
    96.5 1411.58   108.5  1411.5   112.6 1411.36   116.6 1410.97   125.7 1409.74
   128.7 1409.13130.18531408.718   132.7 1408.02   136.5 1408.23137.65521408.532
   140.8 1409.33   144.8 1411.32   148.8 1413.71   152.9 1415.63   156.9 1416.85
     165 1417.93     169 1418.23   189.1 1418.41   213.3 1418.83   236.9 1418.82
#Mann= 3 ,0,0
       0     .07       0130.1853    .045       0137.6552     .07       0
#XS Ineff= 2 , 0
              75    1414
Permanent Ineff=
       F       F
Bank Sta=130.1853,137.6552
XS Rating Curve= 0 ,0
Exp/Cntr(USF)=0,0
Exp/Cntr=0.3,0.1

Type RM Length L Ch R = 1 ,564     ,90,90,90
XS GIS Cut Line= 2
2187565.29575213717086.6871243442187441.24100622717292.152797255
#Sta/Elev= 30
       0 1410.36    12.3 1410.29    25.9 1410.47      45 1409.95    49.2 1409.62
    54.3 1408.86      59 1408.29    66.7 1407.61    82.3 1407.06   102.8 1407.22
   113.3 1407.66   115.1 1407.64  117.64 1407.35   119.7 1407.06     122 1407.15
  123.941407.344   129.1 1407.75   138.4 1407.79   142.5 1408.07   149.2 1408.98
   157.1 1409.78   161.8  1410.5   165.8 1411.34   171.6 1412.97   185.1 1417.93
   189.8  1419.2   195.6 1420.39   200.7 1420.72   218.9 1420.91240.0119 1420.35
#Mann= 4 ,-1,0
       0     .07       0      60      .1       0  117.64    .045       0
  123.94     .07       0
Bank Sta=117.64,123.94
XS Rating Curve= 0 ,0
Exp/Cntr(USF)=0,0
Exp/Cntr=0.3,0.1

Type RM Length L Ch R = 1 ,474     ,177.4,177.4,177.4
XS GIS Cut Line= 2
2187523.42852189717038.207724837 2187363.0935157717230.021920843
#Sta/Elev= 30
       0 1414.19    18.6  1412.2    41.3 1411.37    61.2 1410.16    73.7 1408.15
    82.1 1407.28    86.8 1406.95    98.6 1406.33   103.8 1406.17   111.1 1406.09
   118.6 1406.32   123.6 1406.13   126.5 1405.89     129 1405.83   132.2 1406.11
     135 1406.25   144.6  1406.2   160.3 1405.94   165.5 1406.12   169.1 1406.66
     172 1407.32   175.9 1408.62   183.3  1411.9   191.8 1416.19   198.4 1418.89
     202 1420.13     206 1420.91   217.1 1421.12   225.9 1421.13     250 1420.66
#Mann= 5 ,-1,0
       0      .1       0   123.6    .045       0   132.2      .1       0
     140     .06       0     200     .07       0
Bank Sta=123.6,132.2
XS Rating Curve= 0 ,0
Exp/Cntr(USF)=0,0
Exp/Cntr=0.3,0.1

Type RM Length L Ch R = 1 ,296     ,180.9,180.9,180.9
XS GIS Cut Line= 2
2187417.98074136716908.3584271022187249.73149223 717133.20765406
#Sta/Elev= 30
       0 1415.49      11 1415.14    27.6 1414.89    43.1 1414.98    49.7 1414.66
    56.4 1414.09      66  1412.5    83.1 1408.08    87.6 1407.34    95.9 1406.51
   115.9  1405.3     119 1404.78   121.9 1404.48   125.9 1404.71   130.5 1405.11
     139 1405.24   176.2 1405.19     190 1405.39   196.2 1405.69   205.9 1406.85
   210.9    1408   220.8 1410.95   230.8  1414.7   235.8 1415.93   239.1  1416.5
   247.6 1417.35   253.3 1417.57   273.3 1417.89   276.2 1417.87   280.8 1417.58
#Mann= 5 ,-1,0
       0      .1       0     119    .045       0   125.9      .1       0
     140     .06       0     230     .08       0
Bank Sta=119,125.9
XS Rating Curve= 0 ,0
Exp/Cntr(USF)=0,0
Exp/Cntr=0.3,0.1

Type RM Length L Ch R = 1 ,115     ,,,
XS GIS Cut Line= 2
2187175.51111197716834.2899571982187236.60164558717142.910508131
#Sta/Elev= 30
       0 1419.65    15.2 1419.26    26.9 1417.87    30.3 1417.72    47.8 1417.56
    72.3 1418.49   100.8 1416.69   106.4 1415.42   121.2 1411.02   129.4 1411.03
   133.4 1410.76   137.5 1410.08     146 1406.92  153.521404.877   157.9 1404.27
     162 1404.31  166.071404.877   174.2 1408.16   178.3 1409.41   183.4  1410.5
   202.7 1412.43   223.1 1411.98   227.2 1412.11   231.3 1412.56   239.4 1414.57
   243.5  1415.3   247.6 1415.62   255.8  1415.1   272.1  1415.5   314.6 1414.43
#Mann= 4 ,-1,0
       0     .06       0  153.52    .045       0  166.07     .08       0
     260     .07       0
Bank Sta=153.52,166.07
XS Rating Curve= 0 ,0
Exp/Cntr(USF)=0,0
Exp/Cntr=0.3,0.1
LCMann Table=0

Chan Stop Cuts=-1
Use User Specified Reach Order=0
Composite Channel Slope=5